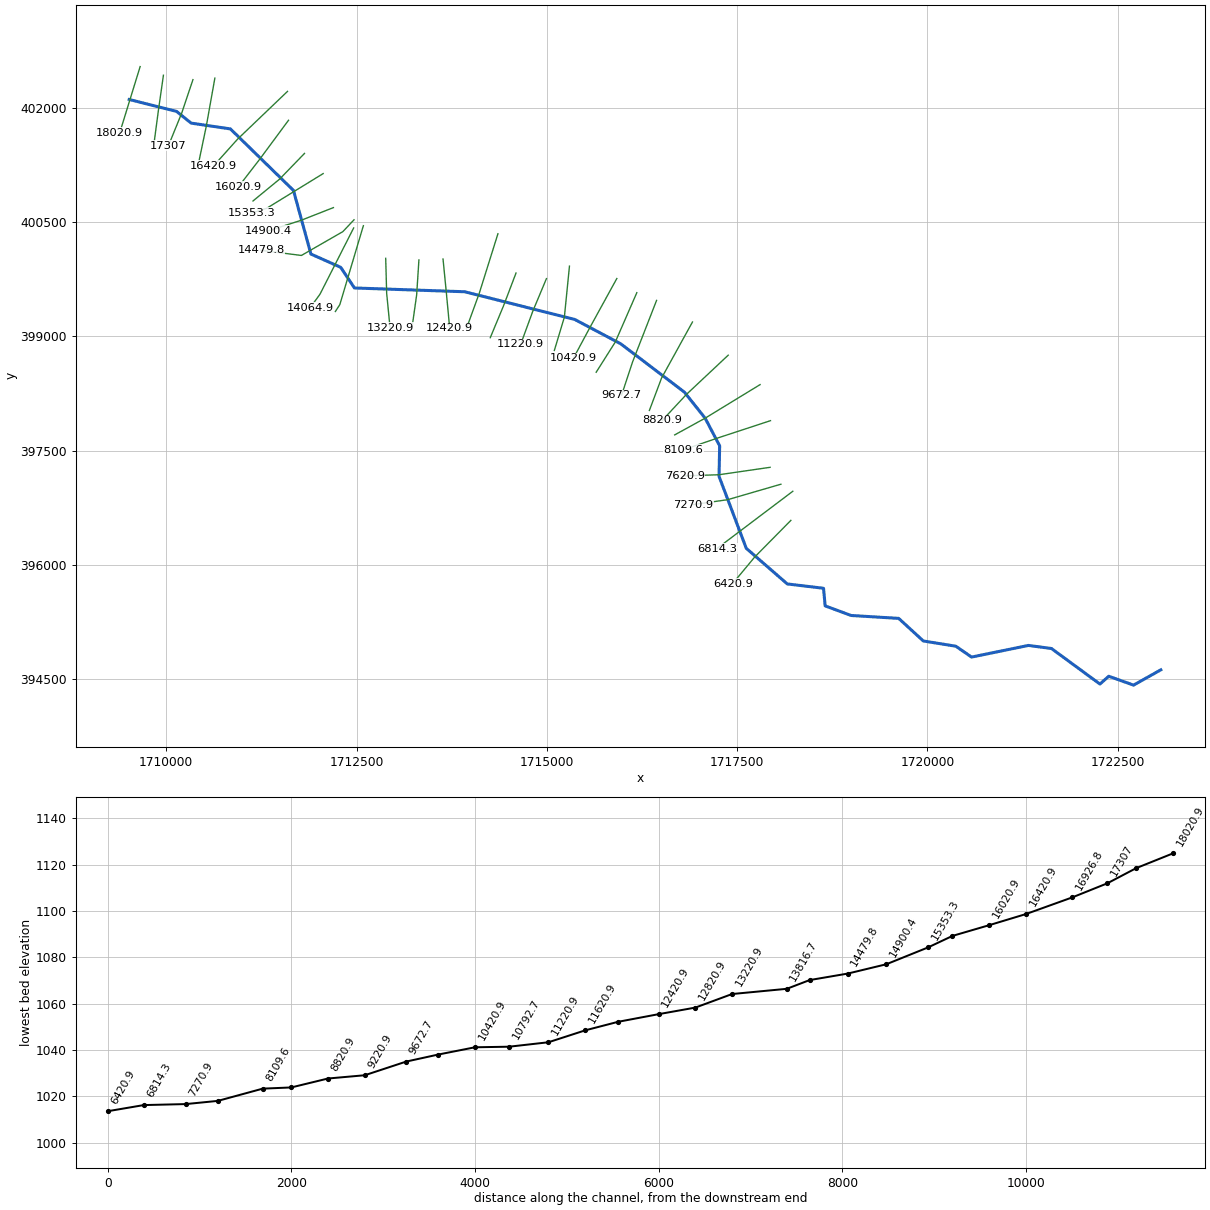
--- SttRdFrk.prj (project) ---

Proj Title=SttRdFrk
Current Plan=p01
Geom File=g01
Flow File=f01
Plan File=p01
DSS Export Rating Curves=0
DSS Export Rating Curve Sorted=0
DSS Export Volume Flow Curves=0
DXF OffsetX=0
DXF OffsetY=0
DXF ScaleX=0
DXF ScaleY=0

--- SttRdFrk.p01 (plan) ---

Plan Title=Floodplain
Program Version=4.00
Geom File=g01
Flow File=f01
K Sum by GR=0
Std Step Tol=0.01
Critical Tol=0.01
Num of Std Step Trials=20
Max Error Tol=0.3
Flow Tol Ratio=0.001
Split Flow NTrial=30
Split Flow Tol=0.02
Split Flow Ratio=0.02
Log Output Level=0
Friction Slope Method=1
Unsteady Friction Slope Method=2
Unsteady Bridges Friction Slope Method=1
Global Log Level=0
CheckData=False
Run HTab=0
Run UNet=0
Run PostProcess=0
UNET Theta=0
UNET Theta Warmup=0
UNET ZTol=0
UNET ZSATol=0
UNET MxIter=0
UNET MaxInSteps=0
UNET DtIC=0
UNET DtMin=0
UNET MaxCRTS=0
UNET WFStab=0
UNET SFStab=0
UNET WFX=0
UNET SFX=0
UNET DSS MLevel=0
UNET DZMax Abort=0
UNET Convert EG Bridges=0
UNET Use Existing IB Tables=0
UNET Froude Limit=0
UNET Froude Power=0
Write IC File=0
Echo Input=False
Echo Output=False
Write Detailed=0

--- SttRdFrk.f01 (steady flow) ---

Flow Title=NFF Regression Equation
Program Version=4.00
Number of Profiles=1
Profile Names=P100yr
River Rch & RM=SttRdFrk,Main      ,18020.9
443.3514
River Rch & RM=SttRdFrk,Main      ,16420.9
478.3275
River Rch & RM=SttRdFrk,Main      ,16020.9
548.7133
River Rch & RM=SttRdFrk,Main      ,14479.8
594.0086
River Rch & RM=SttRdFrk,Main      ,14064.9
925.8749
River Rch & RM=SttRdFrk,Main      ,13816.7
929.4883
River Rch & RM=SttRdFrk,Main      ,12820.9
1030.433
River Rch & RM=SttRdFrk,Main      ,10420.9
1137.642
River Rch & RM=SttRdFrk,Main      ,6814.3
1244.267
River Rch & RM=SttRdFrk,Main      ,6420.9
1438.099
River Rch & RM=SttRdFrk,Main      ,5072.8
1519.545
River Rch & RM=SttRdFrk,Main      ,276.1
1662.020
Boundary for River Rch & Prof#=SttRdFrk,Main      ,1
Up Type=0
Dn Type=3
Dn Slope=0.003339

--- SttRdFrk.g01 (geometry) ---

Geom Title=USGS 3m DEM
Program Version=4.00

River Reach=SttRdFrk     ,Main
Reach XY= 30
     1709513.552      402110.683     1710135.456      401954.478
     1710327.090      401800.413     1710843.201      401724.137
     1711671.466      400916.337     1711900.576      400081.474
     1712291.912      399907.082     1712472.140      399636.030
     1713921.522      399586.423     1715367.433      399222.275
     1715971.371      398902.683     1716806.256      398269.507
     1717079.569      397926.913     1717270.191      397563.587
     1717262.243      397162.602     1717619.622      396218.562
     1718158.971      395750.486     1718634.972      395693.636
     1718656.315      395462.362     1718997.640      395336.443
     1719621.966      395298.423     1719945.698      395001.834
     1720372.975      394932.733     1720579.723      394790.385
     1721326.941      394943.432     1721629.565      394902.620
     1722265.851      394436.069     1722381.576      394538.629
     1722707.902      394422.187     1723065.512      394622.866

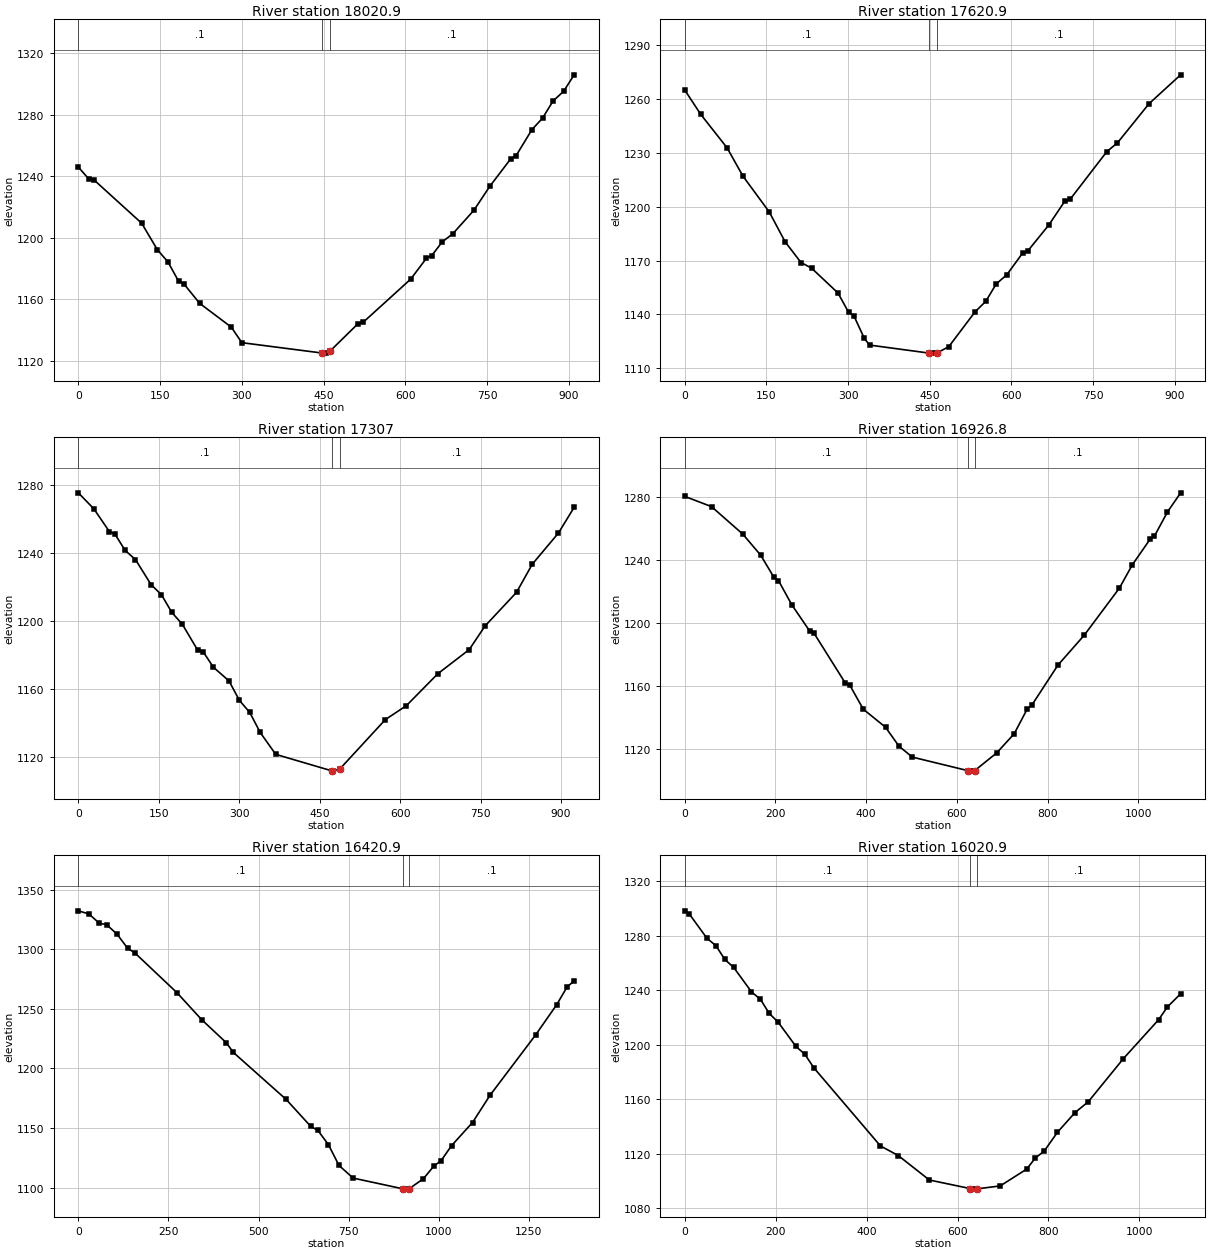
Type RM Length L Ch R = 1 ,18020.9,396.424,400,403.8
XS GIS Cut Line= 3
     1709657.335      402542.483     1709523.107      402107.733
     1709388.878      401672.983
#Sta/Elev= 30
       0 1245.93    19.4 1238.08    29.0 1237.49   116.2 1209.42   145.2 1192.10
   164.6 1184.19   183.9 1171.73   193.6 1169.99   222.7 1157.27   280.7 1141.81
   300.1 1131.70   447.5 1124.95   455.0 1124.90   462.5 1126.42   513.1 1143.97
   522.8 1144.98   609.9 1173.00   638.9 1186.63   648.6 1188.38   668.0 1197.29
   687.3 1202.56   726.1 1217.86   755.1 1233.37   793.8 1251.39   803.5 1253.38
   832.6 1270.34   851.9 1277.71   871.3 1288.92   890.6 1295.18   910.0 1305.93
#Mann= 3 , 0 , 0
       0     0.1       0   447.5   0.045       0   462.5     0.1       0
Bank Sta=   447.5,   462.5
Exp/Cntr=0.3,0.1

Type RM Length L Ch R = 1 ,17620.9,318.959,313.881,308.124
XS GIS Cut Line= 3
     1709963.054      402428.588     1709898.414      401977.303
     1709838.425      401526.433
#Sta/Elev= 30
       0 1264.74    29.1 1251.30    77.6 1232.67   106.7 1216.96   155.2 1196.95
   184.3 1180.40   213.4 1168.90   232.8 1165.77   281.3 1151.98   300.7 1141.31
   310.4 1139.39   329.8 1126.70   339.5 1123.00   448.4 1118.56   455.9 1118.53
   463.4 1118.67   484.9 1122.13   533.3 1141.54   552.7 1147.27   572.0 1156.98
   591.4 1162.06   620.4 1174.11   630.1 1175.37   668.8 1189.81   697.8 1202.93
   707.5 1203.92   775.2 1230.55   794.6 1235.38   852.7 1257.17   910.7 1273.21
#Mann= 3 , 0 , 0
       0     0.1       0   448.4   0.045       0   463.4     0.1       0
Bank Sta=   448.4,   463.4
Exp/Cntr=0.3,0.1

Type RM Length L Ch R = 1 ,17307,375.544,380.223,385.044
XS GIS Cut Line= 3
     1710351.082      402371.213     1710202.655      401930.525
     1710029.363      401504.835
#Sta/Elev= 30
       0 1275.63    29.1 1266.16    58.1 1252.75    67.8 1251.61    87.2 1241.80
   106.6 1236.37   135.6 1221.67   155.0 1215.71   174.4 1205.26   193.8 1198.41
   222.8 1182.99   232.5 1182.28   251.9 1173.06   280.9 1165.05   300.3 1153.62
   319.7 1146.46   339.1 1134.74   368.1 1121.84   473.2 1112.10   474.8 1111.98
   488.2 1113.44   572.6 1142.31   611.7 1150.47   670.4 1169.26   729.0 1183.47
   758.4 1197.32   817.1 1217.10   846.4 1233.62   895.3 1251.99   924.6 1267.12
#Mann= 3 , 0 , 0
       0     0.1       0   473.2   0.045       0   488.2     0.1       0
Bank Sta=   473.2,   488.2
Exp/Cntr=0.3,0.1

Type RM Length L Ch R = 1 ,16926.8,520.909,505.896,500.502
XS GIS Cut Line= 3
     1710638.778      402390.765     1710526.434      401761.190
     1710433.461      401316.715
#Sta/Elev= 30
       0 1280.40    59.0 1273.91   127.9 1256.45   167.3 1243.11   196.8 1228.91
   206.6 1226.96   236.1 1211.52   275.5 1194.89   285.3 1193.39   354.2 1161.76
   364.0 1160.47   393.6 1145.27   442.7 1133.80   472.3 1121.79   501.8 1114.83
   624.7 1106.20   629.7 1105.92   639.7 1106.31   687.8 1117.46   726.5 1129.65
   755.5 1145.51   765.1 1147.69   823.1 1173.29   881.1 1192.28   958.4 1222.10
   987.3 1237.07  1026.0 1253.10  1035.6 1255.06  1064.6 1270.54  1093.6 1282.68
#Mann= 3 , 0 , 0
       0     0.1       0   624.7   0.045       0   639.7     0.1       0
Bank Sta=   624.7,   639.7
Exp/Cntr=0.3,0.1

Type RM Length L Ch R = 1 ,16420.9,398.738,400,398.606
XS GIS Cut Line= 3
     1711593.046      402216.856     1710936.154      401588.609
     1710624.243      401241.362
#Sta/Elev= 30
       0 1332.14    29.3 1329.54    58.6 1321.64    78.2 1320.59   107.5 1312.57
   136.8 1300.72   156.4 1296.97   273.7 1263.46   342.1 1240.88   410.5 1221.52
   430.0 1213.39   576.6 1173.94   645.1 1151.24   664.6 1147.99   693.9 1135.99
   723.3 1118.54   762.4 1107.97   901.5 1098.89   909.0 1098.70   916.5 1098.71
   957.6 1107.48   986.8 1118.20  1006.2 1122.44  1035.4 1135.14  1093.7 1154.58
  1142.3 1177.44  1268.8 1228.06  1327.1 1253.33  1356.3 1268.39  1375.7 1273.33
#Mann= 3 , 0 , 0
       0     0.1       0   901.5   0.045       0   916.5     0.1       0
Bank Sta=   901.5,   916.5
Exp/Cntr=0.3,0.1

Type RM Length L Ch R = 1 ,16020.9,402.079,400,394.508
XS GIS Cut Line= 3
     1711606.424      401837.824     1711228.390      401326.629
     1710950.086      400966.843
#Sta/Elev= 30
       0 1298.16     9.8 1295.88    48.9 1277.94    68.5 1272.59    88.0 1262.47
   107.6 1256.61   146.7 1238.67   166.3 1233.23   185.8 1222.84   205.4 1216.43
   244.5 1198.62   264.1 1192.89   283.7 1183.00   430.4 1125.60   469.5 1118.56
   538.0 1100.59   628.3 1094.28   635.8 1093.90   643.3 1094.10   693.9 1096.26
   751.9 1108.56   771.3 1116.81   790.6 1121.81   819.7 1135.61   858.4 1150.10
   887.4 1157.96   964.8 1189.68  1042.3 1218.26  1061.6 1227.61  1090.7 1237.28
#Mann= 3 , 0 , 0
       0     0.1       0   628.3   0.045       0   643.3     0.1       0
Bank Sta=   628.3,   643.3
Exp/Cntr=0.3,0.1

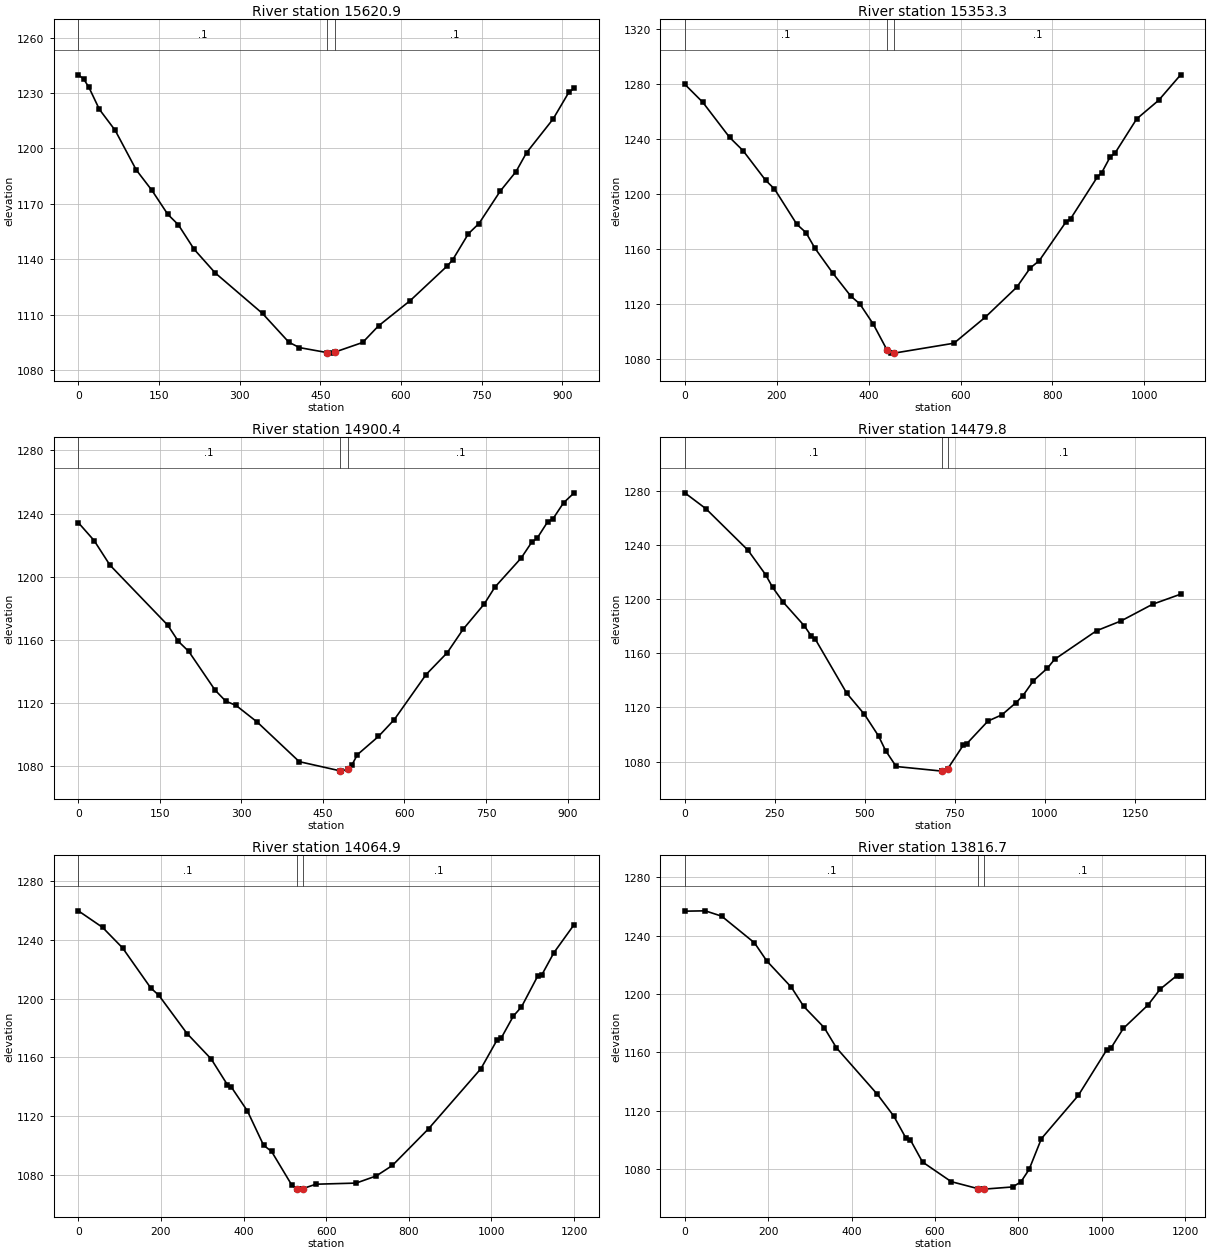
Type RM Length L Ch R = 1 ,15620.9,288.551,267.573,271.086
XS GIS Cut Line= 3
     1711816.253      401402.507     1711489.393      401065.195
     1711139.732      400778.236
#Sta/Elev= 30
       0 1239.86     9.8 1237.64    19.6 1233.13    39.1 1221.19    68.5 1209.82
   107.6 1188.44   137.0 1177.28   166.4 1164.34   185.9 1158.75   215.3 1145.47
   254.4 1132.69   342.5 1110.71   391.4 1095.19   411.0 1092.26   462.2 1089.57
   469.7 1089.26   477.2 1089.84   528.7 1095.03   558.2 1104.01   617.2 1117.70
   686.0 1136.44   695.9 1139.65   725.4 1153.90   745.0 1159.39   784.4 1176.87
   813.9 1187.50   833.5 1197.74   882.7 1215.89   912.2 1230.45   922.0 1232.57
#Mann= 3 , 0 , 0
       0     0.1       0   462.2   0.045       0   477.2     0.1       0
Bank Sta=   462.2,   477.2
Exp/Cntr=0.3,0.1

Type RM Length L Ch R = 1 ,15353.3,428.958,452.946,438.341
XS GIS Cut Line= 3
     1712061.262      401137.730     1711321.036      400682.892
     1711120.372      400620.463
#Sta/Elev= 30
       0 1279.62    39.0 1266.61    97.6 1241.00   126.9 1231.36   175.7 1209.94
   195.2 1203.53   244.0 1177.79   263.6 1171.88   283.1 1160.54   322.1 1142.40
   361.2 1125.70   380.7 1120.10   410.0 1105.43   440.5 1086.29   449.0 1084.26
   455.5 1084.26   585.7 1091.46   654.0 1110.40   722.4 1132.18   751.7 1146.12
   771.2 1151.38   829.8 1179.76   839.5 1181.87   897.5 1212.13   907.0 1215.22
   926.1 1227.09   935.7 1229.33   983.4 1254.48  1031.2 1267.99  1079.0 1286.50
#Mann= 3 , 0 , 0
       0     0.1       0   440.5   0.045       0   455.5     0.1       0
Bank Sta=   440.5,   455.5
Exp/Cntr=0.3,0.1

Type RM Length L Ch R = 1 ,14900.4,415.86,420.557,425.254
XS GIS Cut Line= 3
     1712196.188      400691.140     1711772.859      400524.847
     1711337.597      400384.743
#Sta/Elev= 30
       0 1234.23    29.0 1222.94    58.1 1207.39   164.5 1169.36   183.9 1159.15
   203.2 1152.73   251.6 1128.24   271.0 1121.35   290.3 1118.54   329.0 1108.07
   406.4 1083.00   481.3 1077.21   484.0 1077.01   496.3 1078.40   503.5 1081.04
   513.2 1087.38   552.1 1098.96   581.3 1109.66   639.7 1138.12   678.6 1151.94
   707.8 1166.76   746.7 1182.77   766.1 1193.35   814.8 1211.93   834.2 1221.94
   844.0 1224.39   863.4 1234.80   873.2 1236.69   892.6 1246.80   912.1 1253.11
#Mann= 3 , 0 , 0
       0     0.1       0   481.3   0.045       0   496.3     0.1       0
Bank Sta=   481.3,   496.3
Exp/Cntr=0.3,0.1

Type RM Length L Ch R = 1 ,14479.8,420.372,414.892,428.108
XS GIS Cut Line= 4
     1712467.049      400531.279     1712319.726      400375.503
     1711775.874      400063.064     1711245.229      400129.952
#Sta/Elev= 30
       0 1278.60    58.5 1266.88   175.4 1236.21   224.2 1218.18   243.8 1208.77
   273.2 1197.82   332.0 1180.24   351.6 1172.61   361.4 1170.86   449.6 1130.53
   498.6 1114.97   537.8 1098.96   557.4 1088.17   586.8 1076.40   714.2 1072.98
     715 1072.98     730 1074.74   773.0 1092.11   782.8 1093.25   841.6 1109.96
   880.5 1114.60   919.4 1123.54   938.9 1128.83   968.0 1139.80  1006.9 1149.11
  1026.4 1155.53  1143.1 1176.71  1211.1 1183.94  1298.7 1196.28  1376.5 1203.71
#Mann= 3 , 0 , 0
       0     0.1       0     715   0.045       0     730     0.1       0
Bank Sta=     715,     730
Exp/Cntr=0.3,0.1

Type RM Length L Ch R = 1 ,14064.9,239.433,248.268,257.097
XS GIS Cut Line= 3
     1712462.067      400423.675     1712020.286      399555.041
     1711887.876      399372.472
#Sta/Elev= 30
       0 1259.88    58.5 1248.62   107.2 1234.56   175.4 1207.25   194.9 1202.29
   263.1 1176.23   321.6 1158.87   360.6 1141.41   370.3 1139.75   409.3 1123.43
   448.3 1100.12   467.8 1095.82   516.5 1072.99   528.2 1070.42   536.0 1070.17
   543.2 1070.50   575.0 1073.52   672.4 1074.29   721.1 1079.16   760.1 1086.30
   847.8 1111.35   974.5 1152.31  1013.7 1171.95  1023.6 1173.17  1053.0 1188.17
  1072.6 1194.38  1111.8 1215.36  1121.6 1216.10  1151.0 1231.32  1200.1 1250.52
#Mann= 3 , 0 , 0
       0     0.1       0   528.2   0.045       0   543.2     0.1       0
Bank Sta=   528.2,   543.2
Exp/Cntr=0.3,0.1

Type RM Length L Ch R = 1 ,13816.7,593.082,595.765,600.037
XS GIS Cut Line= 3
     1712589.757      400453.896     1712280.480      399417.818
     1712221.793      399327.296
#Sta/Elev= 30
       0 1256.71    49.1 1256.95    88.5 1253.28   167.1 1235.03   196.6 1222.64
   255.6 1204.60   285.1 1191.53   334.2 1177.02   363.7 1163.13   462.0 1131.25
   501.3 1116.34   530.8 1101.10   540.6 1100.30   570.1 1084.97   638.9 1071.53
   702.9 1066.74   717.6 1066.40   717.9 1066.40   786.4 1067.90   806.0 1071.36
   825.7 1079.86   855.2 1100.96   943.6 1130.51  1012.4 1161.97  1022.3 1163.10
  1051.8 1176.47  1110.7 1192.43  1140.1 1203.33  1179.3 1212.44  1189.1 1212.15
#Mann= 3 , 0 , 0
       0     0.1       0   702.9   0.045       0   717.9     0.1       0
Bank Sta=   702.9,   717.9
Exp/Cntr=0.3,0.1

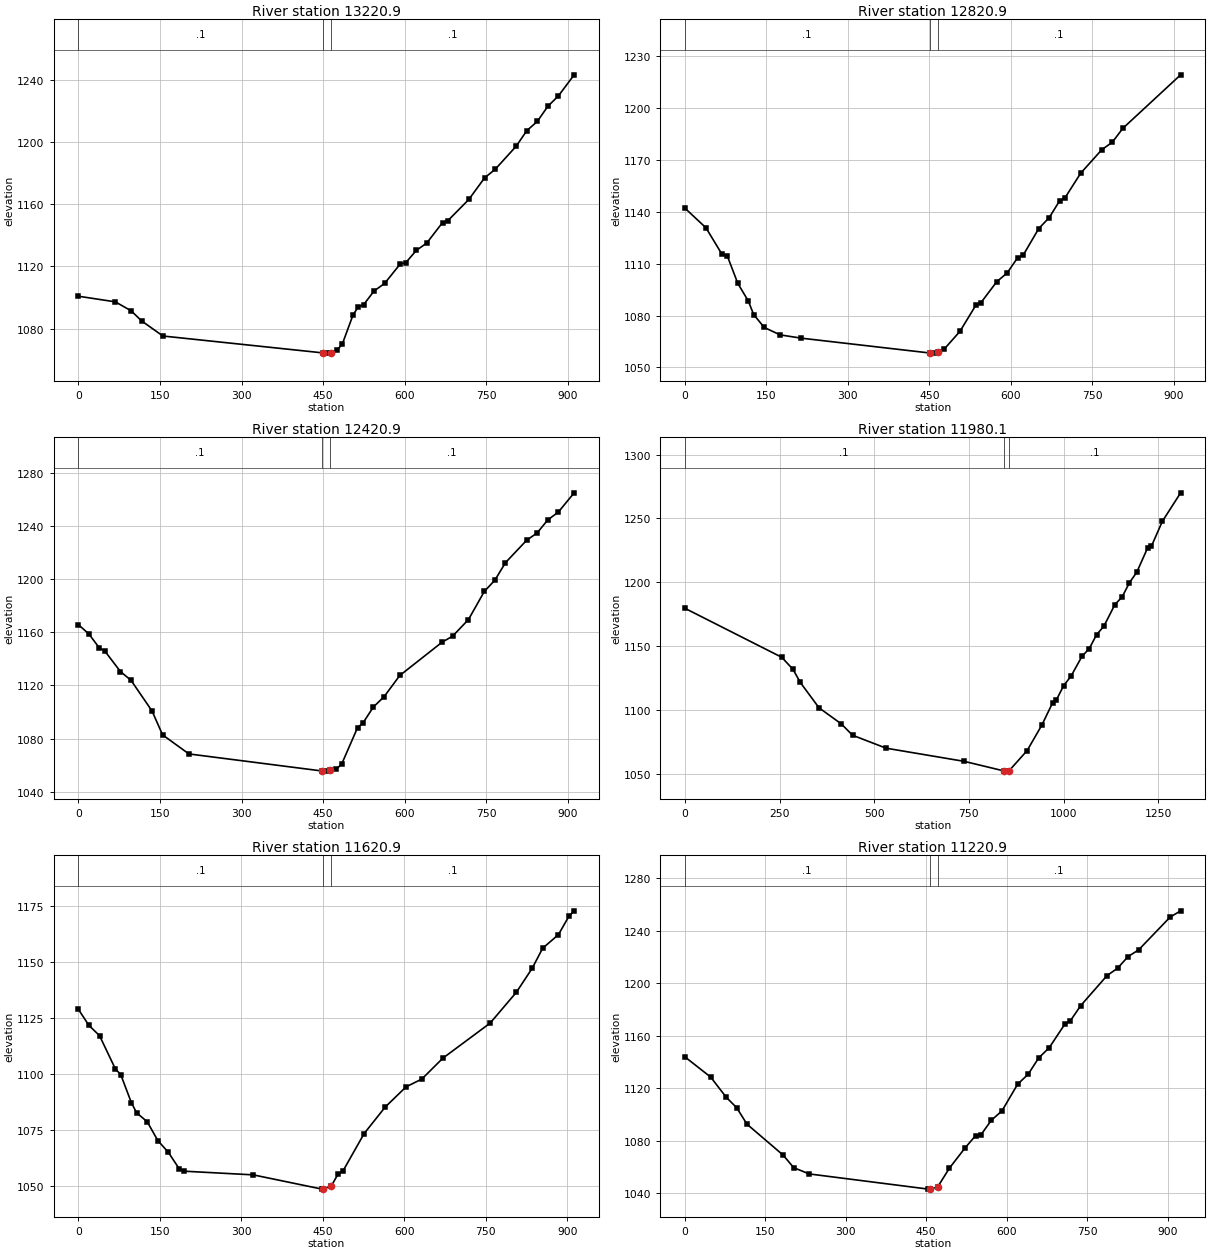
Type RM Length L Ch R = 1 ,13220.9,401.999,400,394.697
XS GIS Cut Line= 3
     1712883.099      400025.285     1712895.593      399569.088
     1712939.944      399116.498
#Sta/Elev= 30
       0 1100.82    68.0 1097.19    97.1 1091.40   116.5 1084.85   155.4 1075.18
   448.9 1064.32   456.4 1064.15   463.9 1064.55   475.7 1066.01   485.4 1070.31
   504.7 1088.67   514.4 1094.03   524.1 1095.29   543.4 1104.17   562.8 1109.07
   591.8 1121.70   601.5 1122.32   620.9 1130.28   640.2 1135.06   669.2 1148.24
   678.9 1149.44   717.6 1163.17   746.6 1177.10   766.0 1182.57   804.7 1197.52
   824.0 1207.44   843.4 1213.44   862.7 1223.15   882.1 1229.86   911.1 1243.45
#Mann= 3 , 0 , 0
       0     0.1       0   448.9   0.045       0   463.9     0.1       0
Bank Sta=   448.9,   463.9
Exp/Cntr=0.3,0.1

Type RM Length L Ch R = 1 ,12820.9,396.36,400,405.269
XS GIS Cut Line= 3
     1713319.442      400004.447     1713289.941      399547.300
     1713226.188      399097.340
#Sta/Elev= 30
       0 1142.20    39.0 1130.76    68.2 1115.59    78.0 1114.70    97.5 1098.68
   117.0 1088.36   126.7 1080.63   146.2 1073.14   175.4 1068.85   214.4 1066.94
   450.6 1058.38   458.1 1058.29   465.6 1058.68   477.4 1060.60   506.4 1070.87
   535.5 1085.89   545.1 1087.48   574.1 1099.56   593.5 1104.74   612.8 1113.56
   622.5 1114.78   651.5 1130.35   670.8 1136.69   690.2 1146.56   699.8 1148.14
   728.8 1162.41   767.5 1175.94   786.9 1180.29   806.2 1188.30   912.6 1219.26
#Mann= 3 , 0 , 0
       0     0.1       0   450.6   0.045       0   465.6     0.1       0
Bank Sta=   450.6,   465.6
Exp/Cntr=0.3,0.1

Type RM Length L Ch R = 1 ,12420.9,451.112,440.762,430.39
XS GIS Cut Line= 3
     1713636.193      400016.438     1713680.775      399563.790
     1713723.656      399109.549
#Sta/Elev= 30
       0 1165.74    19.4 1158.67    38.7 1148.14    48.4 1146.00    77.4 1130.38
    96.8 1123.82   135.5 1100.67   154.8 1082.75   203.2 1068.39   447.3 1055.58
   454.8 1055.45   462.3 1056.03   474.3 1056.98   484.0 1060.84   513.1 1088.21
   522.8 1091.54   542.2 1103.75   561.6 1111.35   590.7 1127.44   668.4 1152.49
   687.8 1157.06   716.9 1169.56   746.1 1190.74   765.5 1199.23   784.9 1212.37
   823.7 1229.19   843.1 1234.76   862.6 1244.53   882.0 1250.42   911.1 1264.93
#Mann= 3 , 0 , 0
       0     0.1       0   447.3   0.045       0   462.3     0.1       0
Bank Sta=   447.3,   462.3
Exp/Cntr=0.3,0.1

Type RM Length L Ch R = 1 ,11980.1,359.822,359.238,358.035
XS GIS Cut Line= 3
     1714357.383      400347.736     1714109.961      399559.079
     1713944.306      399106.155
#Sta/Elev= 30
       0 1179.67   255.8 1141.30   285.4 1131.91   305.0 1121.55   354.2 1101.75
   413.3 1089.09   442.8 1080.25   531.4 1070.11   738.0 1059.77   841.6 1052.36
   845.8 1052.15   856.6 1052.63   903.7 1068.28   942.3 1088.11   971.2 1105.82
   980.9 1107.92  1000.2 1119.13  1019.5 1126.51  1048.4 1141.99  1067.7 1148.15
  1087.0 1158.96  1106.3 1165.66  1135.2 1182.49  1154.5 1188.60  1173.8 1199.69
  1193.1 1207.91  1222.0 1227.15  1231.7 1228.25  1260.6 1247.72  1308.8 1270.03
#Mann= 3 , 0 , 0
       0     0.1       0   841.6   0.045       0   856.6     0.1       0
Bank Sta=   841.6,   856.6
Exp/Cntr=0.3,0.1

Type RM Length L Ch R = 1 ,11620.9,400.744,400,401.082
XS GIS Cut Line= 3
     1714594.758      399831.496     1714431.516      399403.005
     1714256.912      398983.515
#Sta/Elev= 30
       0 1128.73    19.5 1121.51    39.0 1116.96    68.3 1102.04    78.0 1099.60
    97.6 1087.07   107.3 1082.50   126.8 1078.54   146.3 1070.14   165.9 1064.83
   185.4 1057.64   195.1 1056.45   321.9 1054.82   448.8 1048.45     451 1048.48
     466 1049.92   477.9 1055.08   487.5 1056.66   526.2 1073.24   564.9 1085.05
   603.5 1094.11   632.5 1097.58   671.2 1106.90   758.2 1122.54   806.6 1136.33
   835.6 1147.00   854.9 1155.94   883.9 1162.02   903.2 1170.19   912.9 1172.65
#Mann= 3 , 0 , 0
       0     0.1       0     451   0.045       0     466     0.1       0
Bank Sta=     451,     466
Exp/Cntr=0.3,0.1

Type RM Length L Ch R = 1 ,11220.9,421.593,428.226,429.598
XS GIS Cut Line= 3
     1714994.580      399758.729     1714815.515      399330.939
     1714657.095      398898.497
#Sta/Elev= 30
       0 1144.06    48.3 1128.59    77.3 1113.20    96.6 1105.38   115.9 1092.76
   183.6 1069.11   202.9 1059.68   231.9 1054.88   454.1 1043.31   456.3 1043.33
   471.3 1044.93   493.2 1059.22   522.5 1074.72   542.1 1084.05   551.9 1084.56
   571.5 1095.80   591.1 1102.78   620.5 1123.20   640.1 1130.78   659.7 1143.18
   679.3 1150.95   708.7 1169.08   718.5 1171.29   738.1 1183.05   787.1 1205.88
   806.7 1211.48   826.3 1220.35   845.9 1225.42   904.7 1250.40   924.3 1255.19
#Mann= 3 , 0 , 0
       0     0.1       0   456.3   0.045       0   471.3     0.1       0
Bank Sta=   456.3,   471.3
Exp/Cntr=0.3,0.1

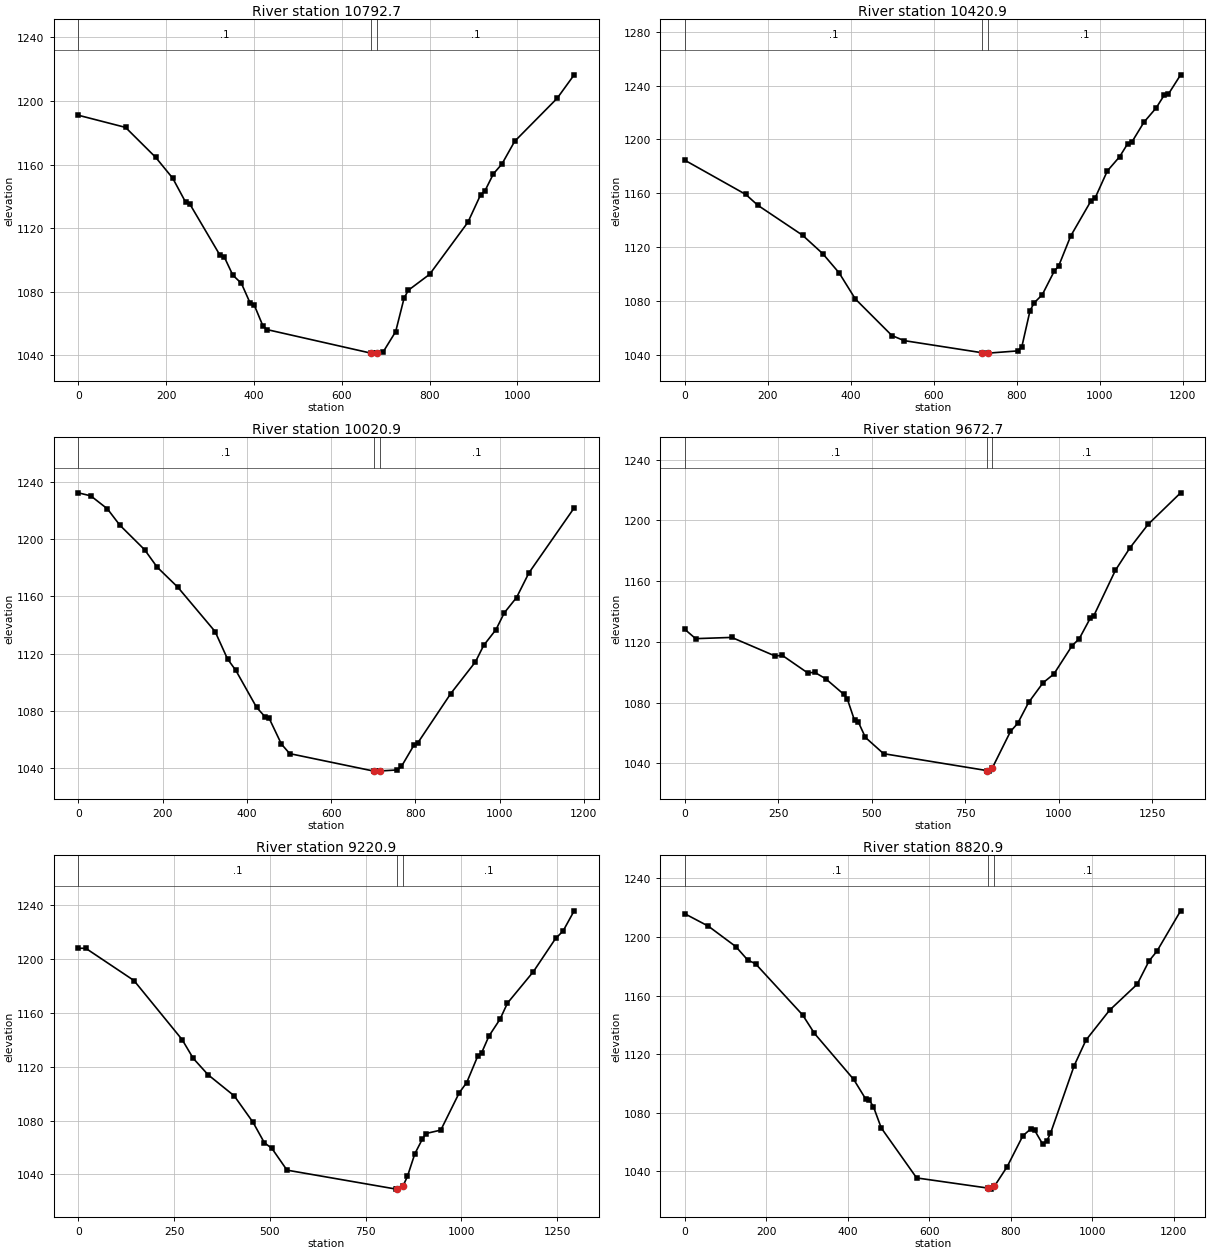
Type RM Length L Ch R = 1 ,10792.7,380.645,371.774,367.243
XS GIS Cut Line= 3
     1715297.050      399922.412     1715229.994      399251.495
     1715098.417      398815.982
#Sta/Elev= 30
       0 1191.08   107.5 1183.43   175.9 1164.66   215.0 1151.45   244.3 1136.39
   254.1 1135.12   322.5 1103.03   332.2 1102.00   351.8 1090.48   371.3 1085.33
   390.9 1073.12   400.6 1071.65   420.2 1058.64   430.0 1056.18   665.4 1041.44
   674.3 1041.39   680.4 1041.39   693.6 1041.86   722.7 1054.92   742.0 1076.14
   751.7 1080.99   800.1 1091.00   887.2 1123.74   916.3 1141.12   925.9 1143.42
   945.3 1154.22   964.7 1160.38   993.7 1174.67  1090.5 1201.75  1129.2 1216.51
#Mann= 3 , 0 , 0
       0     0.1       0   665.4   0.045       0   680.4     0.1       0
Bank Sta=   665.4,   680.4
Exp/Cntr=0.3,0.1

Type RM Length L Ch R = 1 ,10420.9,398.514,400,396.346
XS GIS Cut Line= 3
     1715919.233      399760.109     1715570.369      399125.545
     1715347.546      398710.744
#Sta/Elev= 30
       0 1184.53   146.8 1159.12   176.1 1151.02   283.8 1128.77   332.7 1114.99
   371.9 1100.80   411.0 1081.39   499.1 1054.22   528.4 1050.45   716.6 1041.42
   731.6 1041.14   802.6 1042.80   812.4 1046.02   832.0 1072.63   841.9 1078.47
   861.5 1084.53   890.9 1102.35   900.7 1105.63   930.1 1128.21   979.2 1154.42
   989.0 1156.51  1018.4 1176.58  1047.9 1187.08  1067.5 1196.85  1077.3 1197.93
  1106.7 1212.82  1136.1 1223.41  1155.8 1233.07  1165.6 1233.71  1195.0 1247.99
#Mann= 3 , 0 , 0
       0     0.1       0   716.6   0.045       0   731.6     0.1       0
Bank Sta=   716.6,   731.6
Exp/Cntr=0.3,0.1

Type RM Length L Ch R = 1 ,10020.9,345.987,348.172,355.276
XS GIS Cut Line= 3
     1716182.118      399574.543     1715898.731      398925.406
     1715647.972      398529.680
#Sta/Elev= 30
       0 1232.20    29.5 1230.09    68.9 1221.04    98.4 1209.67   157.4 1192.48
   186.9 1180.40   236.1 1166.34   324.6 1135.40   354.1 1116.27   373.8 1108.30
   423.0 1082.53   442.7 1076.05   452.5 1075.11   482.0 1056.86   501.7 1050.21
   700.8 1038.05   708.3 1038.00   715.8 1038.10   757.1 1038.83   766.9 1041.28
   796.1 1055.90   805.9 1057.80   884.0 1092.15   942.5 1114.24   962.1 1125.77
   991.3 1136.76  1010.9 1148.43  1040.1 1159.15  1069.4 1176.33  1176.8 1221.68
#Mann= 3 , 0 , 0
       0     0.1       0   700.8   0.045       0   715.8     0.1       0
Bank Sta=   700.8,   715.8
Exp/Cntr=0.3,0.1

Type RM Length L Ch R = 1 ,9672.7,454.799,451.828,452.161
XS GIS Cut Line= 4
     1716441.520      399473.020     1716290.697      399086.391
     1716125.091      398661.863     1715982.321      398229.967
#Sta/Elev= 30
       0 1128.30    29.0 1122.18   125.5 1122.99   241.3 1110.77   260.6 1111.18
   328.1 1099.70   347.4 1099.97   376.4 1095.83   424.7 1085.62   434.4 1082.53
   453.8 1068.36   463.5 1067.52   482.9 1057.14   531.4 1046.46   807.5 1035.34
   812.5 1034.97   822.5 1037.22   870.7 1061.08   890.0 1066.40   919.1 1080.16
   957.8 1093.13   986.8 1098.91  1035.2 1117.45  1054.6 1122.14  1083.6 1135.45
  1093.3 1137.16  1151.4 1167.25  1190.1 1181.94  1238.5 1197.37  1325.6 1218.17
#Mann= 3 , 0 , 0
       0     0.1       0   807.5   0.045       0   822.5     0.1       0
Bank Sta=   807.5,   822.5
Exp/Cntr=0.3,0.1

Type RM Length L Ch R = 1 ,9220.9,406.999,400,391.202
XS GIS Cut Line= 4
     1716912.985      399189.336     1716730.653      398858.814
     1716507.266      398453.871     1716347.066      398028.417
#Sta/Elev= 30
       0 1208.05    19.4 1208.02   145.2 1184.08   271.0 1140.16   300.0 1126.24
   338.8 1114.04   407.0 1098.38   456.2 1078.69   485.7 1063.53   505.4 1059.33
   544.8 1043.17   830.1 1029.06   832.5 1029.08   847.5 1031.23   859.3 1038.55
   878.6 1055.34   898.0 1066.09   907.7 1070.39   946.4 1072.93   994.7 1100.73
  1014.1 1108.26  1043.1 1128.08  1052.7 1130.16  1072.1 1142.79  1101.1 1155.35
  1120.5 1167.32  1188.2 1190.68  1246.2 1215.36  1265.5 1220.77  1294.6 1235.86
#Mann= 3 , 0 , 0
       0     0.1       0   832.5   0.045       0   847.5     0.1       0
Bank Sta=   832.5,   847.5
Exp/Cntr=0.3,0.1

Type RM Length L Ch R = 1 ,8820.9,404.62,400,392.848
XS GIS Cut Line= 4
     1717383.048      398754.093     1717165.097      398549.592
     1716834.503      398239.402     1716517.746      397899.724
#Sta/Elev= 30
       0 1215.89    57.8 1207.41   125.3 1193.42   154.3 1184.28   173.5 1181.71
   289.2 1146.70   318.2 1134.08   414.6 1102.59   443.6 1089.38   453.2 1088.25
   462.8 1084.04   482.1 1069.46   568.9 1035.31   744.7 1028.33   752.2 1027.65
   759.7 1029.61   790.9 1042.92   829.6 1064.13   849.0 1068.81   858.6 1067.80
   878.0 1058.48   887.7 1060.31   897.3 1065.70   955.4 1111.99   984.4 1129.51
  1042.5 1150.00  1110.2 1167.74  1139.2 1183.64  1158.6 1190.30  1216.7 1217.89
#Mann= 3 , 0 , 0
       0     0.1       0   744.7   0.045       0   759.7     0.1       0
Bank Sta=   744.7,   759.7
Exp/Cntr=0.3,0.1

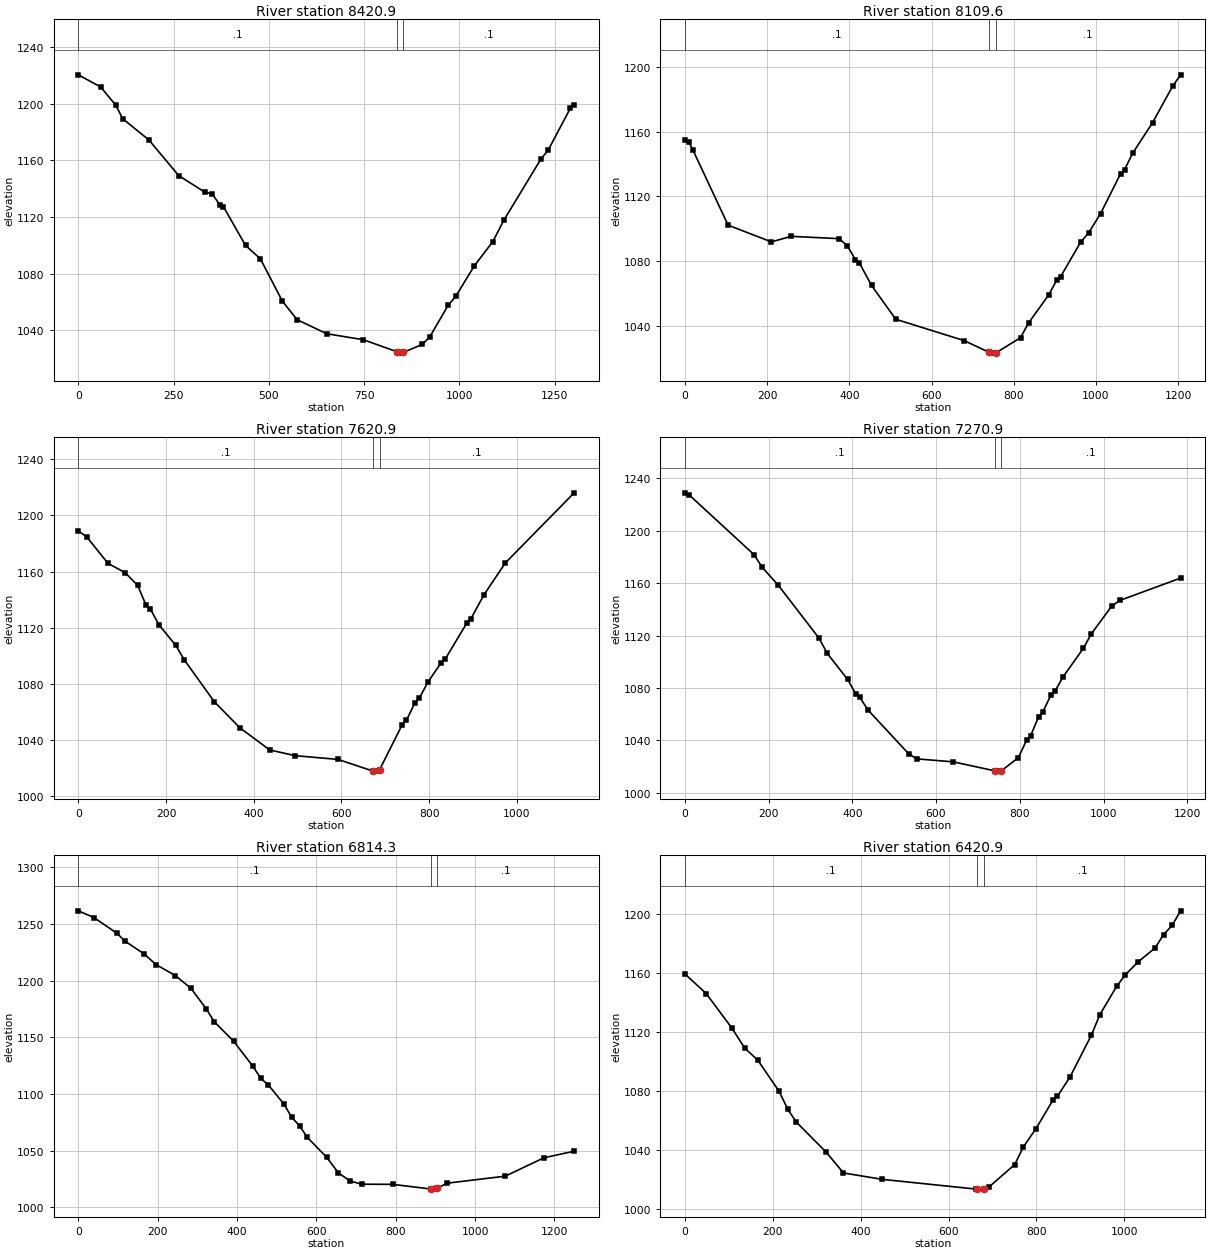
Type RM Length L Ch R = 1 ,8420.9,316.261,311.313,307.445
XS GIS Cut Line= 4
     1717801.034      398367.069     1717467.667      398163.639
     1717079.611      397926.835     1716679.607      397707.119
#Sta/Elev= 30
       0 1220.29    58.6 1211.73    97.6 1199.02   117.2 1189.11   185.5 1174.25
   263.6 1149.08   332.0 1137.49   351.5 1136.21   371.0 1128.62   380.8 1127.25
   438.9 1099.83   477.6 1090.47   535.6 1060.49   574.3 1047.40   651.7 1037.50
   748.4 1033.24   837.6 1024.64   845.1 1023.79   852.6 1024.24   903.4 1030.02
   922.8 1035.43   971.4 1057.82   990.8 1063.91  1039.3 1085.36  1087.9 1102.52
  1117.0 1117.65  1214.1 1160.75  1233.5 1167.21  1291.8 1196.89  1301.5 1199.20
#Mann= 3 , 0 , 0
       0     0.1       0   837.6   0.045       0   852.6     0.1       0
Bank Sta=   837.6,   852.6
Exp/Cntr=0.3,0.1

Type RM Length L Ch R = 1 ,8109.6,492.71,488.687,482.063
XS GIS Cut Line= 4
     1717938.364      397894.076     1717674.524      397807.509
     1717245.886      397666.870     1716794.769      397511.941
#Sta/Elev= 30
       0 1154.95     9.6 1153.48    19.2 1148.90   105.3 1102.25   210.7 1091.91
   258.5 1095.34   375.7 1093.90   395.4 1089.39   415.0 1080.93   424.8 1078.83
   454.2 1065.03   513.0 1044.17   679.8 1030.96   740.8 1023.66   748.3 1023.27
   755.8 1023.29   816.4 1032.81   835.9 1041.90   884.5 1058.98   904.0 1068.09
   913.8 1070.36   962.4 1091.68   981.9 1097.44  1011.1 1109.38  1059.8 1134.01
  1069.5 1136.48  1089.0 1146.56  1137.6 1165.51  1186.3 1187.97  1205.8 1195.01
#Mann= 3 , 0 , 0
       0     0.1       0   740.8   0.045       0   755.8     0.1       0
Bank Sta=   740.8,   755.8
Exp/Cntr=0.3,0.1

Type RM Length L Ch R = 1 ,7620.9,349.272,349.977,352.792
XS GIS Cut Line= 4
     1717932.905      397281.593     1717732.126      397252.477
     1717260.452      397184.077     1716809.557      397169.316
#Sta/Elev= 30
       0 1189.01    19.3 1184.67    67.6 1165.85   106.3 1159.34   135.3 1150.20
   154.6 1135.94   164.2 1133.42   183.6 1122.16   222.3 1107.45   241.8 1097.09
   309.9 1067.43   368.2 1048.86   436.3 1033.06   494.7 1028.97   591.9 1026.33
     672 1018.00   679.5 1017.98     687 1019.02   738.3 1050.87   748.1 1054.14
   767.8 1066.74   777.6 1069.96   797.2 1081.37   826.6 1094.86   836.4 1097.62
   885.4 1123.19   895.2 1126.42   924.7 1143.38   973.7 1166.18  1130.6 1216.07
#Mann= 3 , 0 , 0
       0     0.1       0     672   0.045       0     687     0.1       0
Bank Sta=     672,     687
Exp/Cntr=0.3,0.1

Type RM Length L Ch R = 1 ,7270.9,445.466,456.589,468.152
XS GIS Cut Line= 3
     1718074.991      397059.843     1717375.169      396856.437
     1716924.471      396792.512
#Sta/Elev= 30
       0 1228.81     9.7 1227.44   165.2 1181.69   184.6 1172.10   223.5 1158.21
   320.7 1117.91   340.1 1106.41   388.7 1086.58   408.1 1075.54   417.8 1072.96
   437.3 1063.26   534.4 1029.88   553.9 1025.95   641.3 1023.66   740.9 1016.78
   748.2 1016.60   755.9 1016.87   796.6 1026.88   816.0 1040.13   825.6 1043.41
   845.0 1058.18   854.7 1061.63   874.1 1074.40   883.7 1077.38   903.1 1088.40
   951.5 1110.14   970.9 1121.35  1019.3 1142.35  1038.7 1146.74  1184.0 1163.81
#Mann= 3 , 0 , 0
       0     0.1       0   740.9   0.045       0   755.9     0.1       0
Bank Sta=   740.9,   755.9
Exp/Cntr=0.3,0.1

Type RM Length L Ch R = 1 ,6814.3,390.31,393.434,398.498
XS GIS Cut Line= 3
     1718231.563      396967.432     1717239.943      396219.368
     1717237.035      396212.328
#Sta/Elev= 30
       0 1261.53    39.1 1255.64    97.8 1241.63   117.4 1234.80   166.3 1223.44
   195.6 1214.17   244.5 1204.46   283.6 1193.31   322.8 1174.97   342.3 1163.88
   391.2 1146.64   440.1 1124.45   459.7 1113.87   479.3 1107.84   518.4 1091.11
   537.9 1079.44   557.5 1072.03   577.1 1061.83   626.0 1044.26   655.3 1030.56
   684.6 1023.41   714.0 1020.52   792.2 1020.39   889.9 1016.21   899.8 1016.17
   904.9 1016.95   929.2 1021.40  1075.9 1027.57  1173.7 1043.82  1249.8 1049.59
#Mann= 3 , 0 , 0
       0     0.1       0   889.9   0.045       0   904.9     0.1       0
Bank Sta=   889.9,   904.9
Exp/Cntr=0.3,0.1

Type RM Length L Ch R = 1 ,6420.9,279.966,281.658,281.497
XS GIS Cut Line= 3
     1718205.468      396584.702     1717732.375      396105.693
     1717441.661      395756.180
#Sta/Elev= 30
       0 1159.19    48.8 1145.81   107.3 1122.37   136.6 1108.83   165.9 1100.82
   214.7 1079.61   234.2 1067.51   253.7 1058.87   322.0 1038.39   361.0 1024.46
   448.8 1020.13   663.5 1013.51   665.8 1013.52   680.8 1013.92   692.6 1015.13
   750.6 1030.16   770.0 1042.00   799.0 1054.46   837.7 1073.85   847.4 1076.22
   876.4 1089.45   924.7 1117.57   944.1 1131.53   982.8 1150.89  1002.1 1158.54
  1031.1 1167.25  1069.8 1176.69  1089.2 1185.72  1108.5 1191.94  1127.9 1201.81
#Mann= 3 , 0 , 0
       0     0.1       0   665.8   0.045       0   680.8     0.1       0
Bank Sta=   665.8,   680.8
Exp/Cntr=0.3,0.1