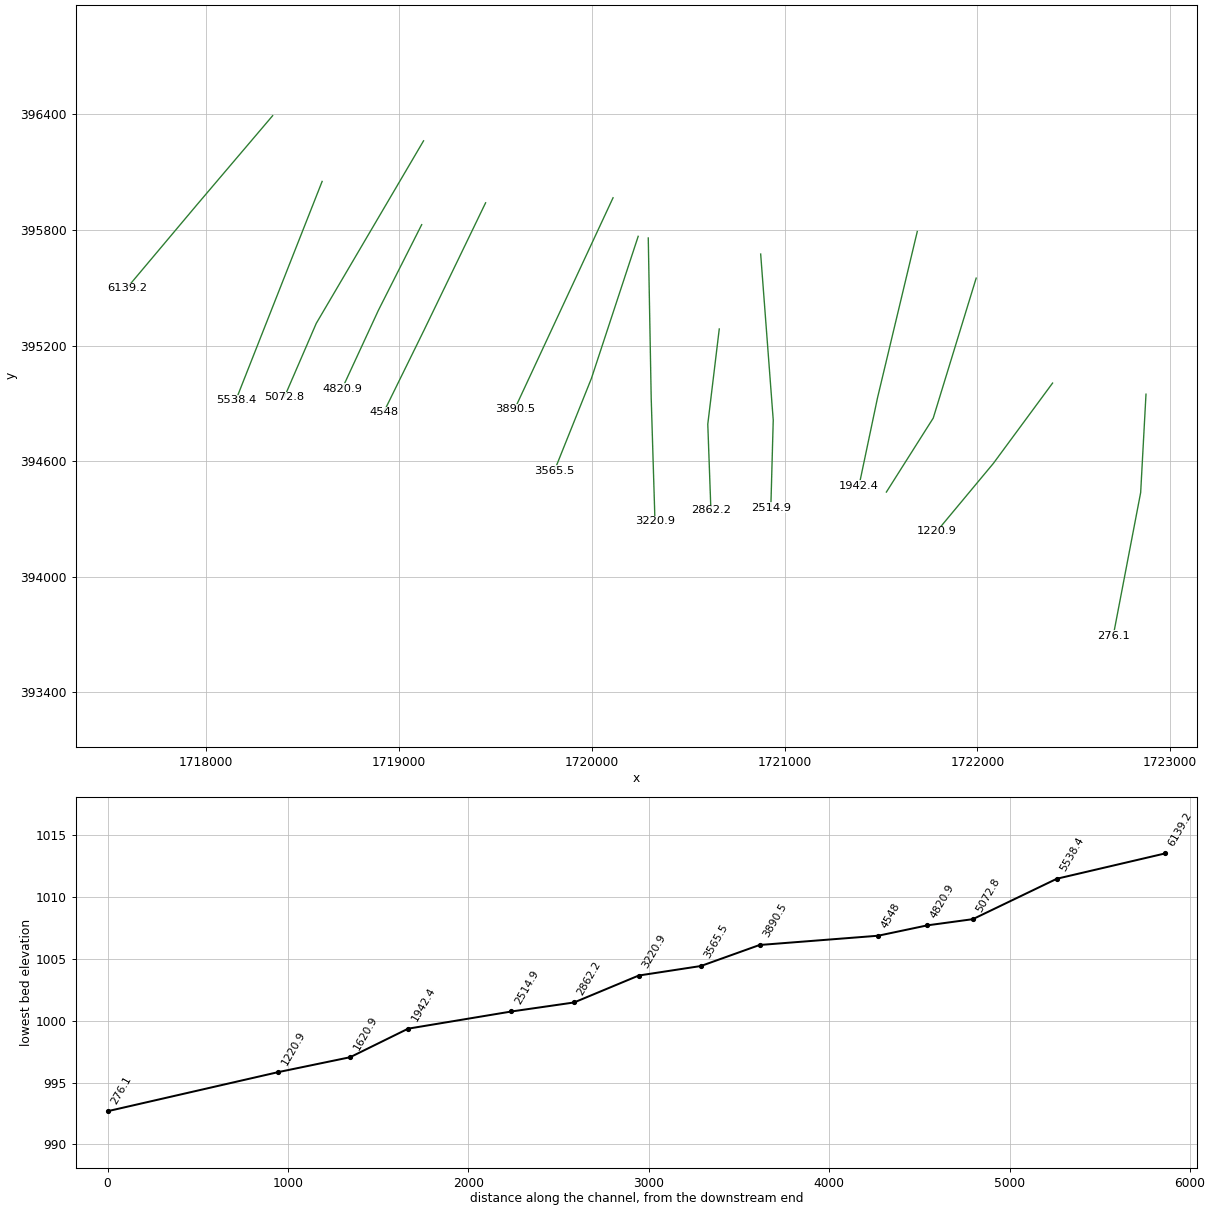
HEC-RAS study SttRdFrk.prj: SttRdFrk

--- SttRdFrk.g01 (geometry) --- (continued)

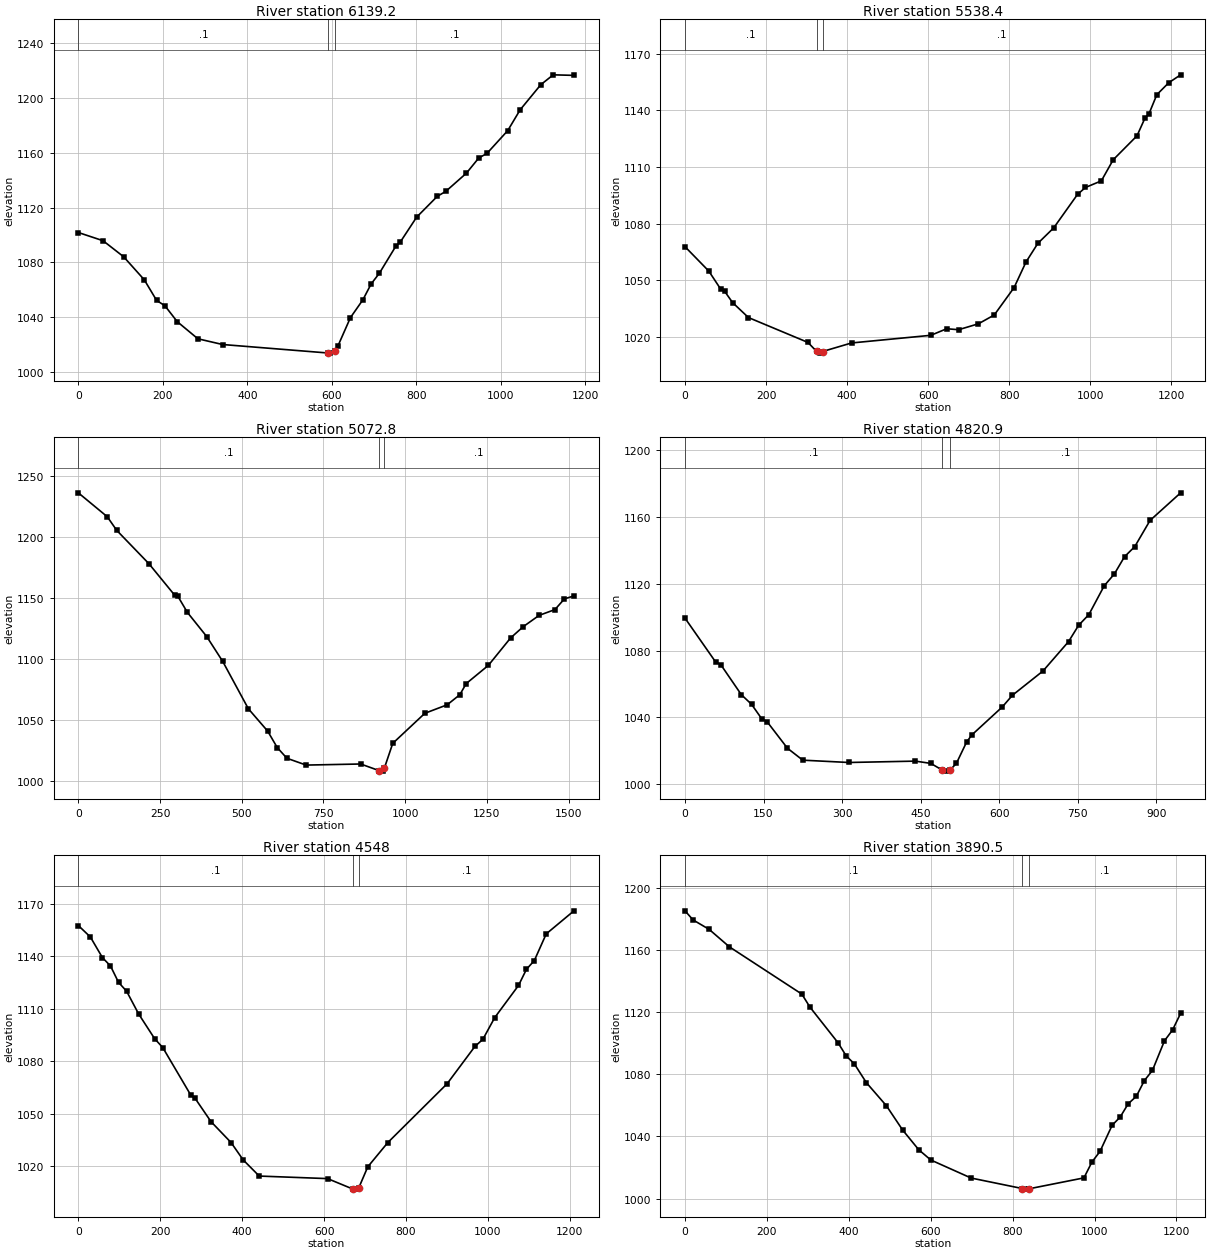
Type RM Length L Ch R = 1 ,6139.2,593.967,600.8,607.467
XS GIS Cut Line= 3
     1718344.642      396393.337     1717953.213      395932.320
     1717587.880      395497.399
#Sta/Elev= 30
       0 1101.76    58.5 1095.76   107.3 1084.01   156.1 1067.16   185.3 1052.09
   204.8 1048.22   234.1 1036.56   282.9 1024.04   341.4 1019.85   591.6 1013.62
   595.0 1013.55   606.6 1015.09   614.6 1018.99   643.9 1039.52   673.3 1052.51
   692.9 1064.15   712.5 1072.03   751.7 1091.96   761.5 1094.61   800.6 1113.01
   849.6 1128.27   869.2 1131.76   918.2 1145.12   947.5 1156.24   967.1 1159.66
  1016.1 1176.28  1045.5 1191.51  1094.4 1209.89  1123.8 1217.08  1172.8 1216.68
#Mann= 3 , 0 , 0
       0     0.1       0   591.6   0.045       0   606.6     0.1       0
Bank Sta=   591.6,   606.6
Exp/Cntr=0.3,0.1

Type RM Length L Ch R = 1 ,5538.4,461.986,465.638,453.39
XS GIS Cut Line= 2
     1718601.393      396052.131     1718153.277      394914.605
#Sta/Elev= 30
       0 1067.81    58.7 1054.91    88.0 1045.37    97.8 1044.20   117.4 1038.23
   156.5 1030.32   303.2 1017.17   324.4 1012.47   332.5 1011.50   339.4 1012.36
   410.8 1016.88   606.4 1020.93   645.5 1024.40   674.9 1023.89   723.8 1027.02
   762.9 1031.69   811.8 1046.19   841.2 1059.73   870.5 1069.61   909.6 1077.80
   968.3 1095.49   987.9 1099.15  1027.0 1102.64  1056.3 1113.81  1115.0 1126.49
  1134.6 1135.84  1144.4 1138.07  1163.9 1148.24  1193.3 1154.56  1222.6 1158.74
#Mann= 3 , 0 , 0
       0     0.1       0   324.4   0.045       0   339.4     0.1       0
Bank Sta=   324.4,   339.4
Exp/Cntr=0.3,0.1

Type RM Length L Ch R = 1 ,5072.8,250.478,251.904,254.113
XS GIS Cut Line= 3
     1719127.500      396262.860     1718570.801      395314.732
     1718405.531      394932.002
#Sta/Elev= 30
       0 1236.47    88.4 1216.90   117.8 1205.60   216.0 1178.34   294.5 1152.61
   304.3 1151.75   333.8 1138.37   392.7 1118.64   441.8 1098.21   520.3 1059.35
   579.2 1041.10   608.6 1027.55   638.1 1018.80   697.0 1013.19   863.9 1014.08
   921.2 1008.56   932.6 1008.23   936.2 1010.56   962.0 1031.01  1060.2 1055.66
  1128.6 1062.64  1167.3 1070.91  1186.7 1080.01  1254.6 1094.98  1322.5 1117.44
  1361.2 1126.70  1409.7 1135.95  1458.2 1140.72  1487.3 1149.51  1516.4 1151.93
#Mann= 3 , 0 , 0
       0     0.1       0   921.2   0.045       0   936.2     0.1       0
Bank Sta=   921.2,   936.2
Exp/Cntr=0.3,0.1

Type RM Length L Ch R = 1 ,4820.9,273.054,272.931,272.17
XS GIS Cut Line= 3
     1719117.830      395827.555     1718893.052      395382.397
     1718705.254      394975.974
#Sta/Elev= 30
       0 1099.45    58.7 1073.06    68.4 1071.53   107.6 1053.55   127.1 1047.78
   146.7 1039.01   156.5 1037.46   195.6 1021.46   224.9 1014.30   312.9 1012.91
   440.0 1013.73   469.4 1012.36   491.2 1008.36   498.7 1007.73   506.2 1008.43
   518.2 1012.37   537.6 1025.10   547.4 1029.34   605.8 1046.19   625.2 1053.21
   683.6 1067.77   732.3 1085.35   751.7 1095.19   771.2 1101.59   800.4 1118.80
   819.9 1125.97   839.3 1136.30   858.8 1142.32   888.0 1158.03   946.4 1174.58
#Mann= 3 , 0 , 0
       0     0.1       0   491.2   0.045       0   506.2     0.1       0
Bank Sta=   491.2,   506.2
Exp/Cntr=0.3,0.1

Type RM Length L Ch R = 1 ,4548,656.326,657.45,658.478
XS GIS Cut Line= 3
     1719449.342      395941.019     1719129.233      395278.110
     1718920.308      394852.661
#Sta/Elev= 30
       0 1157.56    29.4 1151.00    58.9 1139.19    78.5 1134.46    98.2 1125.06
   117.8 1120.03   147.2 1107.04   186.5 1092.81   206.1 1087.83   274.8 1060.54
   284.6 1058.96   323.9 1045.47   373.0 1033.50   402.4 1023.62   441.7 1014.36
   608.6 1012.90     670 1006.96   677.3 1006.89     685 1007.76   706.7 1019.62
   755.5 1033.47   900.6 1067.17   968.3 1088.44   987.7 1092.51  1016.7 1104.94
  1074.7 1123.28  1094.1 1132.53  1113.4 1137.55  1142.4 1152.77  1210.1 1165.95
#Mann= 3 , 0 , 0
       0     0.1       0     670   0.045       0     685     0.1       0
Bank Sta=     670,     685
Exp/Cntr=0.3,0.1

Type RM Length L Ch R = 1 ,3890.5,323.976,325.038,324.307
XS GIS Cut Line= 2
     1720110.422      395967.114     1719600.046      394869.806
#Sta/Elev= 30
       0 1185.02    19.7 1179.17    59.0 1173.09   108.2 1161.91   285.3 1131.49
   305.0 1123.16   373.9 1100.13   393.6 1091.76   413.2 1086.75   442.8 1074.59
   491.9 1059.68   531.3 1044.17   570.7 1031.46   600.2 1024.86   698.6 1013.27
     824 1006.50   836.3 1006.14     839 1006.30   974.1 1013.37   993.7 1023.59
  1013.4 1030.41  1042.9 1047.18  1062.6 1052.49  1082.3 1061.05  1102.0 1065.78
  1121.6 1075.89  1141.3 1082.43  1170.8 1101.51  1190.5 1108.45  1210.2 1119.16
#Mann= 3 , 0 , 0
       0     0.1       0     824   0.045       0     839     0.1       0
Bank Sta=     824,     839
Exp/Cntr=0.3,0.1

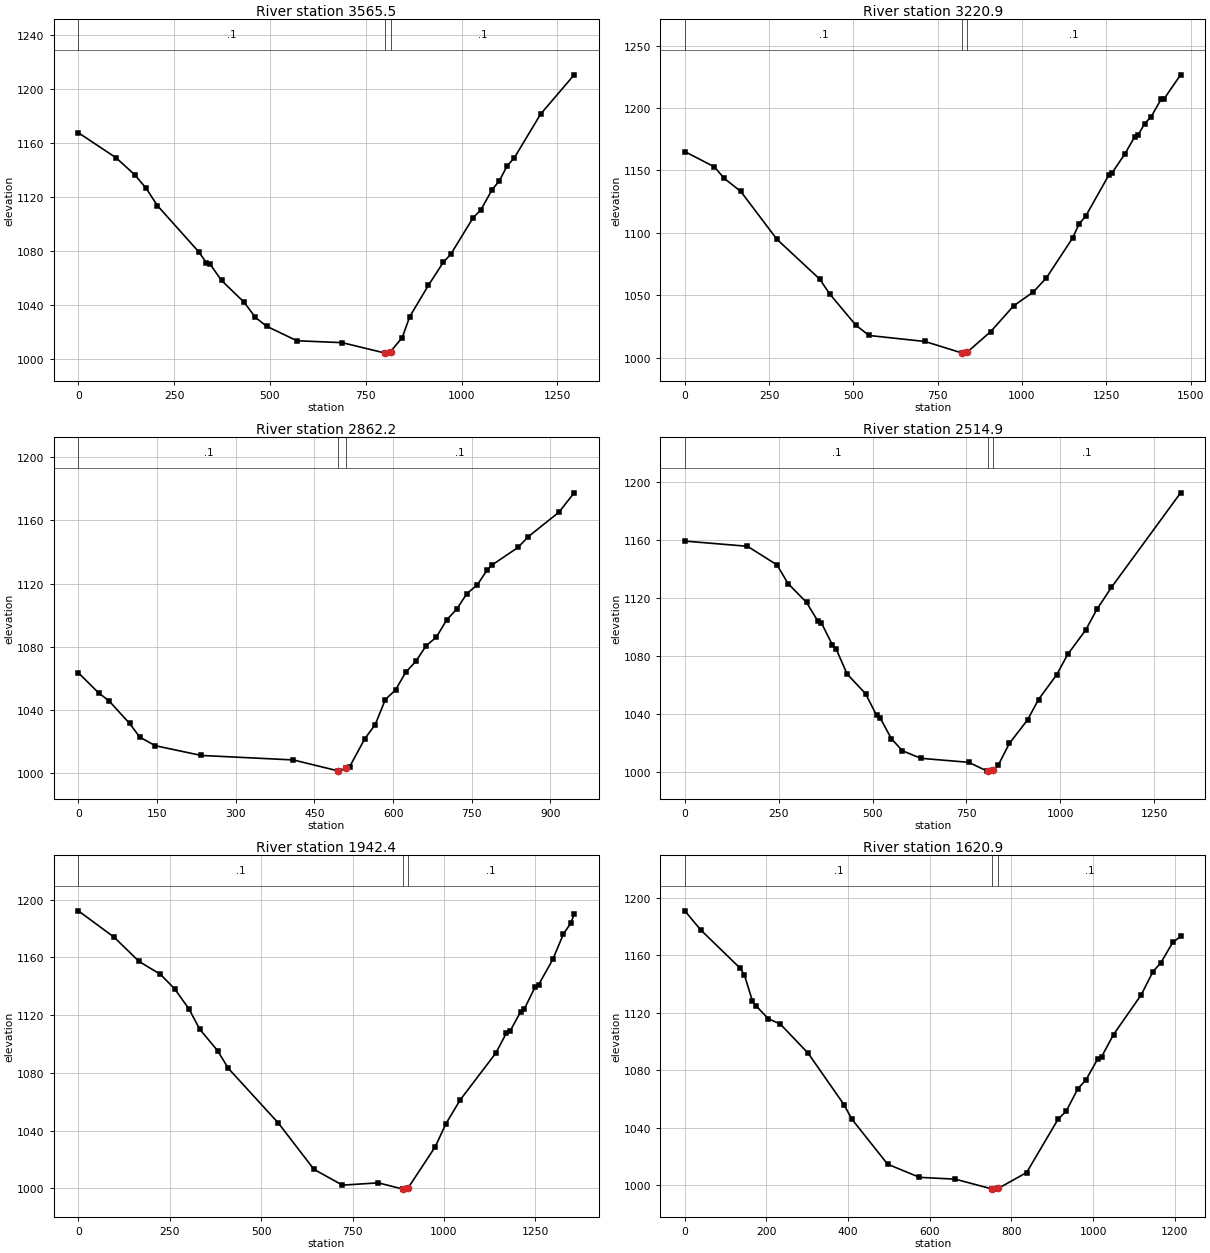
Type RM Length L Ch R = 1 ,3565.5,334.953,344.581,356.231
XS GIS Cut Line= 3
     1720240.898      395767.050     1719998.213      395029.161
     1719805.977      394549.271
#Sta/Elev= 30
       0 1167.83    98.3 1149.28   147.5 1136.55   177.0 1126.62   206.5 1113.73
   314.6 1079.39   334.3 1071.36   344.1 1070.29   373.6 1058.29   432.6 1042.16
   462.1 1030.85   491.6 1024.31   570.3 1013.62   688.3 1012.20   799.7 1004.54
   806.0 1004.44   814.7 1005.62   845.1 1015.94   864.6 1031.45   913.3 1054.65
   952.3 1071.78   971.9 1077.76  1030.4 1104.97  1049.9 1110.38  1079.1 1125.37
  1098.7 1132.27  1118.2 1142.91  1137.7 1149.25  1205.9 1181.50  1293.7 1210.73
#Mann= 3 , 0 , 0
       0     0.1       0   799.7   0.045       0   814.7     0.1       0
Bank Sta=   799.7,   814.7
Exp/Cntr=0.3,0.1

Type RM Length L Ch R = 1 ,3220.9,360.167,358.667,359.05
XS GIS Cut Line= 3
     1720293.089      395758.352     1720308.309      394928.865
     1720327.882      394288.319
#Sta/Elev= 30
       0 1165.10    87.8 1152.86   117.1 1143.59   165.9 1133.23   273.3 1094.82
   400.2 1062.94   429.5 1051.17   507.5 1025.98   546.6 1017.80   712.5 1012.99
   822.1 1003.78   829.6 1003.67   837.1 1004.35   907.3 1020.93   975.3 1041.55
  1033.5 1052.62  1072.4 1063.92  1150.0 1095.80  1169.5 1107.20  1188.9 1113.39
  1256.9 1145.95  1266.6 1147.80  1305.4 1163.32  1334.5 1177.04  1344.2 1178.23
  1363.7 1187.48  1383.1 1193.02  1412.2 1206.82  1421.9 1207.53  1470.5 1226.58
#Mann= 3 , 0 , 0
       0     0.1       0   822.1   0.045       0   837.1     0.1       0
Bank Sta=   822.1,   837.1
Exp/Cntr=0.3,0.1

Type RM Length L Ch R = 1 ,2862.2,343.791,347.326,348.096
XS GIS Cut Line= 3
     1720661.392      395285.794     1720601.852      394791.693
     1720618.035      394344.601
#Sta/Elev= 30
       0 1063.72    39.0 1050.85    58.5 1045.93    97.6 1031.66   117.1 1023.01
   146.4 1017.59   234.2 1011.41   409.9 1008.56   495.4 1001.63   497.7 1001.49
   510.4 1003.49   517.1 1004.26   546.3 1022.11   565.8 1030.86   585.2 1046.74
   604.7 1052.89   624.1 1064.02   643.6 1071.04   663.0 1080.79   682.5 1086.24
   701.9 1097.00   721.4 1104.04   740.8 1113.79   760.3 1119.22   779.7 1128.86
   789.4 1132.03   838.1 1142.95   857.5 1149.71   915.9 1165.17   945.1 1177.48
#Mann= 3 , 0 , 0
       0     0.1       0   495.4   0.045       0   510.4     0.1       0
Bank Sta=   495.4,   510.4
Exp/Cntr=0.3,0.1

Type RM Length L Ch R = 1 ,2514.9,579.275,572.548,566.289
XS GIS Cut Line= 3
     1720876.203      395674.832     1720941.382      394813.124
     1720928.870      394357.237
#Sta/Elev= 30
       0 1159.01   166.9 1155.43   245.5 1142.64   275.0 1129.76   324.1 1116.82
   353.5 1104.31   363.3 1102.90   392.8 1087.70   402.6 1084.98   432.1 1067.60
   481.2 1054.03   510.6 1039.18   520.5 1037.24   549.9 1023.11   579.4 1014.76
   628.5 1009.58   756.1 1006.81   805.2 1000.76   806.8 1000.78   821.8 1001.38
   834.7 1004.89   864.2 1019.82   912.7 1036.05   941.8 1050.03   990.3 1067.12
  1019.4 1081.02  1067.9 1098.02  1097.1 1112.00  1135.9 1127.16  1320.2 1192.21
#Mann= 3 , 0 , 0
       0     0.1       0   806.8   0.045       0   821.8     0.1       0
Bank Sta=   806.8,   821.8
Exp/Cntr=0.3,0.1

Type RM Length L Ch R = 1 ,1942.4,319.932,321.459,313.452
XS GIS Cut Line= 3
     1721688.591      395792.041     1721482.173      394927.840
     1721386.013      394470.240
#Sta/Elev= 30
       0 1192.35    97.6 1174.11   166.0 1157.27   224.6 1148.31   263.6 1138.19
   302.7 1124.29   332.0 1110.24   380.8 1095.42   410.1 1083.15   546.8 1045.27
   644.4 1013.09   722.5 1002.13   820.2 1003.72   886.7  999.47   888.5  999.37
   901.7 1000.10   976.2 1028.77  1005.4 1044.72  1044.4 1061.23  1141.8 1093.70
  1171.0 1107.70  1180.8 1108.96  1210.0 1122.44  1219.7 1124.27  1248.9 1139.29
  1258.7 1141.03  1297.7 1158.66  1326.9 1176.40  1346.4 1183.57  1356.1 1189.81
#Mann= 3 , 0 , 0
       0     0.1       0   886.7   0.045       0   901.7     0.1       0
Bank Sta=   886.7,   901.7
Exp/Cntr=0.3,0.1

Type RM Length L Ch R = 1 ,1620.9,410.387,400,397.337
XS GIS Cut Line= 3
     1721994.089      395549.845     1721771.375      394823.174
     1721528.319      394439.050
#Sta/Elev= 30
       0 1191.10    39.0 1177.78   136.4 1150.89   146.2 1146.21   165.6 1128.30
   175.4 1124.59   204.6 1115.86   233.9 1112.17   302.1 1091.82   389.8 1056.04
   409.2 1045.86   496.9 1014.44   574.9 1005.28   662.6 1004.00   752.5  997.18
   760.0  997.06   767.5  997.53   837.4 1008.64   914.8 1046.01   934.1 1051.33
   963.1 1067.16   982.5 1073.16  1011.5 1087.78  1021.2 1089.46  1050.2 1104.82
  1117.9 1132.45  1146.9 1148.72  1166.2 1154.94  1195.3 1169.05  1214.6 1173.28
#Mann= 3 , 0 , 0
       0     0.1       0   752.5   0.045       0   767.5     0.1       0
Bank Sta=   752.5,   767.5
Exp/Cntr=0.3,0.1

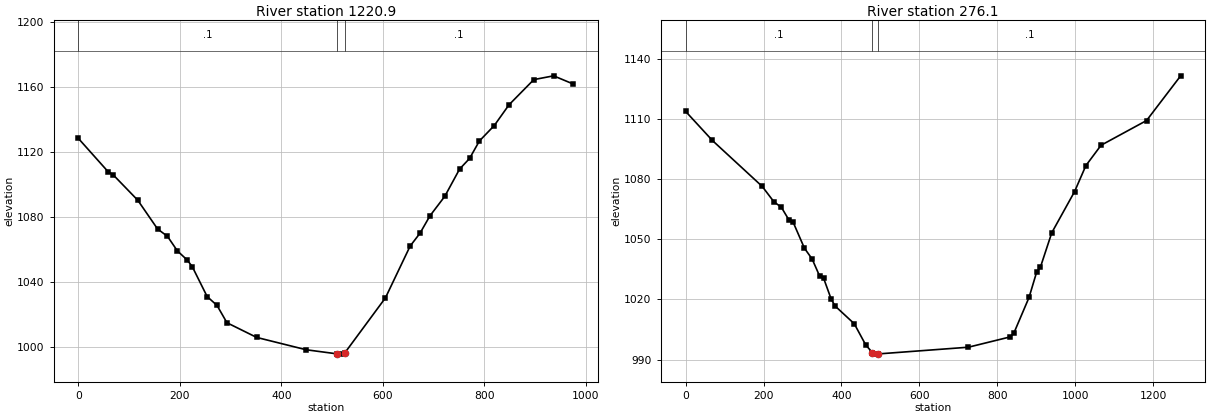
Type RM Length L Ch R = 1 ,1220.9,932.986,944.81,950.635
XS GIS Cut Line= 3
     1722390.411      395004.902     1722083.625      394588.343
     1721790.847      394236.253
#Sta/Elev= 30
       0 1128.45    58.6 1107.98    68.3 1106.16   117.1 1090.44   156.2 1072.74
   175.7 1068.22   195.2 1059.28   214.7 1053.63   224.5 1049.60   253.8 1031.24
   273.3 1025.76   292.8 1015.14   351.4 1006.11   449.0  998.53   509.8  996.01
   517.3  995.85   524.8  996.52   605.0 1030.42   653.7 1062.26   673.2 1070.19
   692.7 1080.82   721.9 1092.80   751.2 1109.61   770.7 1116.06   790.1 1126.83
   819.4 1136.31   848.6 1149.11   897.3 1164.53   936.3 1166.86   975.3 1161.78
#Mann= 3 , 0 , 0
       0     0.1       0   509.8   0.045       0   524.8     0.1       0
Bank Sta=   509.8,   524.8
Exp/Cntr=0.3,0.1

Type RM Length L Ch R = 1 ,276.1,273.155,276.089,278.145
XS GIS Cut Line= 3
     1722874.962      394947.294     1722847.354      394436.489
     1722704.851      393691.496
#Sta/Elev= 30
       0 1113.74    68.9 1099.19   196.7 1076.29   226.3 1068.72   245.9 1065.85
   265.6 1059.45   275.5 1058.68   305.0 1045.48   324.6 1040.14   344.3 1031.45
   354.2 1030.51   373.8 1019.99   383.7 1016.66   432.8 1007.83   462.4  997.20
   479.2  993.49   491.9  992.69   494.2  992.79   725.5  996.14   832.5 1001.27
   842.2 1003.19   881.1 1020.96   900.5 1033.53   910.2 1036.00   939.4 1053.21
   997.8 1073.69  1026.9 1086.68  1065.8 1096.82  1182.5 1109.14  1270.0 1131.43
#Mann= 3 , 0 , 0
       0     0.1       0   479.2   0.045       0   494.2     0.1       0
Bank Sta=   479.2,   494.2
Exp/Cntr=0.3,0.1